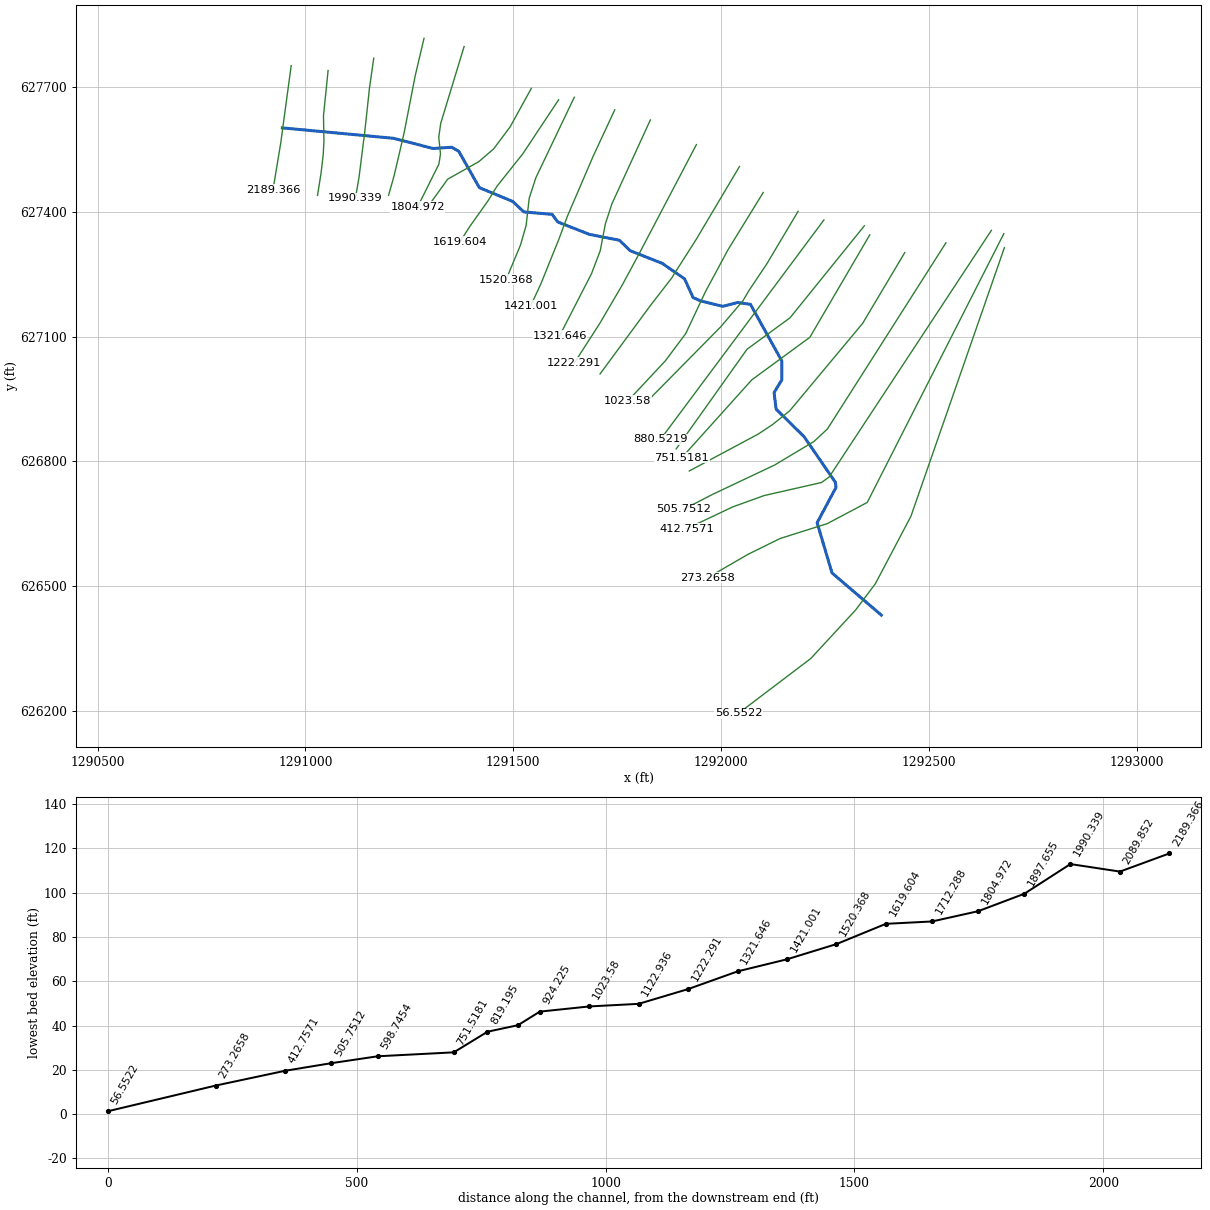
--- 748_ras.prj (project) ---

Proj Title=748
Current Plan=p01
Default Exp/Contr=0.3,0.1
English Units
Geom File=g01
Flow File=f01
Plan File=p01
Y Axis Title=Elevation
X Axis Title(PF)=Main Channel Distance
X Axis Title(XS)=Station
BEGIN DESCRIPTION:
RFD model 748 exported to HEC-RAS
END DESCRIPTION:

--- 748_ras.p01 (plan) ---

Plan Title=Plan 01
Program Version=4.10
Short Identifier=Plan 01
Geom File=g01
Flow File=f01
Subcritical Flow
Calc Critical at every XS
Secant Critical Depth

--- 748_ras.f01 (steady flow) ---

Flow Title=Flow 01
Program Version=5.01
Number of Profiles= 5
Profile Names=10yr,25yr,50yr,100yr,500yr
River Rch & RM=748,22,2189.366
  367.02  434.97  517.79  548.63   637.9
River Rch & RM=748,22,1520.368
  373.56  443.86  528.69  561.65  655.22
River Rch & RM=748,22,1421.001
  378.13  450.09  536.31  570.78   667.4
River Rch & RM=748,22,1321.646
  385.26  459.83  548.27  585.11   686.6
River Rch & RM=748,22,1222.291
  409.57  493.24  589.29  634.61  753.38
River Rch & RM=748,22,1122.936
  431.85  524.11  627.27  680.83   816.4
River Rch & RM=748,22, 1023.58
     442  538.25   644.7  702.15  845.69
River Rch & RM=748,22, 924.225
  443.42  540.23  647.14  705.14  849.81
River Rch & RM=748,22, 819.195
  456.59  558.66  669.86  733.07  888.38
River Rch & RM=748,22,598.7454
  463.29  568.06  681.47  747.38  908.23
River Rch & RM=748,22,505.7512
  466.58   572.7  687.19  754.44  918.05
River Rch & RM=748,22,273.2658
  475.62  585.44  702.92  773.91  945.18
River Rch & RM=748,22, 56.5522
   481.3  593.45  712.83   786.2  962.34
Boundary for River Rch & Prof#=748,22,1
Up Type= 0
Dn Type= 2
Boundary for River Rch & Prof#=748,22,2
Up Type= 0
Dn Type= 2
Boundary for River Rch & Prof#=748,22,2
Up Type= 0
Dn Type= 2
Boundary for River Rch & Prof#=748,22,2
Up Type= 0
Dn Type= 2
Boundary for River Rch & Prof#=748,22,2
Up Type= 0
Dn Type= 2

--- 748_ras.g01 (geometry) ---

Geom Title=748
Program Version=4.10

River Reach=748,22
Reach XY= 30
 1290944.6308094627602.1044001881291212.04455522627577.080353737
1291307.23403487627552.5469797251291352.37543806627555.490982935
 1291369.0581302627545.6776339561291418.61553755627458.338831067
1291498.99446711 627425.101418541291525.47016153 627399.92780742
1291593.78380629 627394.06139338 1291607.0318262627375.906698316
1291683.08527619627345.9759831881291755.70405465627331.746625736
1291781.21875995627306.7225864081291858.25354481627276.301203817
1291912.22696042627239.0104780641291932.83499089627193.869074419
1291950.49901798627186.0183951261292004.47243434627172.770373106
1292039.80048919627182.0930531171292070.71253681 627177.67704536
1292146.27531621627041.2714993211292146.27531493626996.130096316
1292127.62995183626965.2180491391292132.53662491626925.473987699
1292199.75806019626859.2338834851292274.83017299626749.815045729
 1292276.7928423 626737.548360081292231.16076928626652.172229677
1292266.97948775626531.4680423591292385.72100151626429.899882093

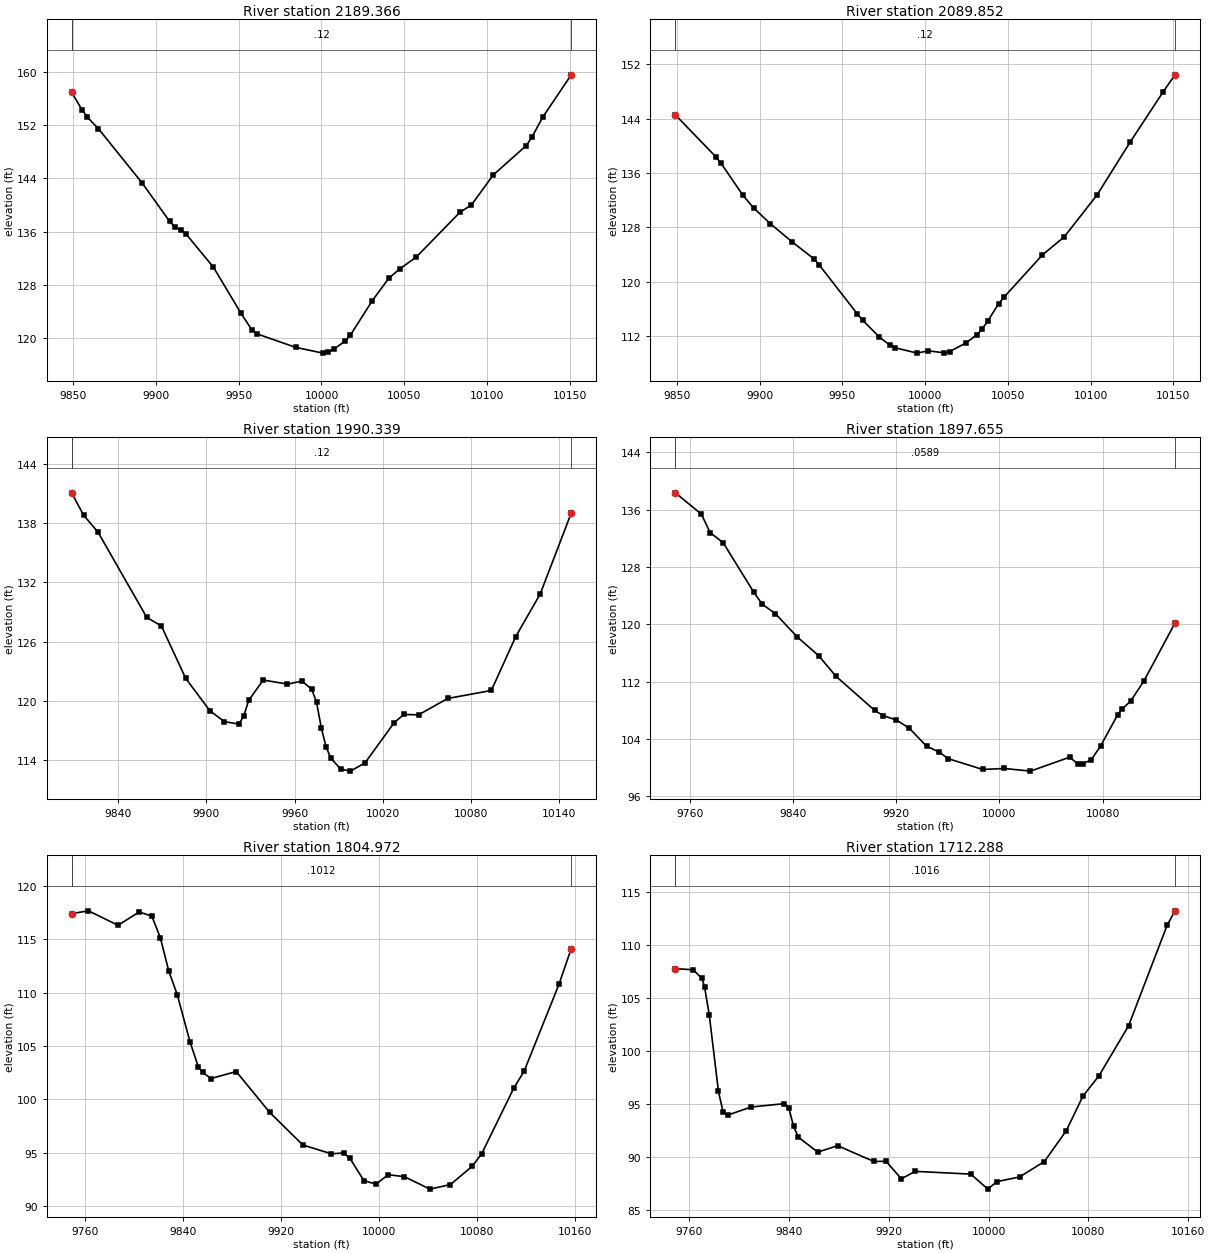
Type RM Length L Ch R = 1 ,2189.366,99.513300,99.513300,99.513300
XS GIS Cut Line= 5
 1290965.8977973627751.6176104611290945.74080125627602.980709514
 1290945.5071187627600.9944083121290941.08820656627567.795406014
 1290922.0808806627452.854960289
#Sta/Elev= 30
9849.003156.94349855.236154.31139858.547153.18589865.169151.46639891.656143.2897
 9908.21137.53339911.521136.64339914.832136.27039918.143135.63059934.697130.6372
9951.252123.75179957.873121.23979961.184120.6024 9984.36118.586710000.91117.7172
10004.22117.884310007.53118.320910014.15119.498610017.46120.4045 10030.7125.5942
10040.66128.956710047.31130.377810057.28132.154510083.89138.938410090.54139.9577
10103.84144.507110123.79148.922610127.12150.151310133.77153.205110150.99159.5633
#Mann= 3 , 0 , 0
9849.003    0.12       09849.003    0.12       010150.99    0.12       0
#XS Ineff= 2 , 0
       0                               0
Bank Sta=9849.003,10150.99
Exp/Cntr=0.3,0.1

Type RM Length L Ch R = 1 ,2089.852,99.513400,99.513400,99.513400
XS GIS Cut Line= 6
1291054.67982956627740.0827080961291043.62163392627631.189547042
1291044.66770285627569.8187877081291043.13409877 627539.73477331
1291037.79942835627493.5241568481291029.25390443627439.762029704
#Sta/Elev= 30
9849.029144.55869873.323 138.4369876.621137.44479889.812132.74369896.407130.8514
  9906.3128.57599919.491 125.8979932.682123.40079935.979122.47799959.061115.2548
9962.342114.31879972.187111.9046 9978.75 110.6619982.032110.2848 9995.17109.5124
10001.74109.852410011.59109.555410014.88109.751310024.73111.0274 10031.3 112.219
10034.59113.112110037.87114.243410044.44116.810210047.73 117.76910070.83123.9543
10084.04126.6169 10103.9132.796710123.83140.542510143.77147.943410150.98150.4579
#Mann= 3 , 0 , 0
9849.029    0.12       09849.029    0.12       010150.98    0.12       0
#XS Ineff= 2 , 0
       09951.372        10044.46       0
Bank Sta=9849.029,10150.98
Exp/Cntr=0.3,0.1

Type RM Length L Ch R = 1 ,1990.339,92.683600,92.683600,92.683600
XS GIS Cut Line= 6
1291164.51071995627769.8391377331291154.37605873627698.825805947
 1291141.3098962627577.9097583441291139.94636065627569.396658391
1291129.25567612 627484.251825721291120.46612206627432.604443148
#Sta/Elev= 30
9808.203141.06589816.279138.82389826.221137.06689859.362128.45599869.304127.5929
9885.849122.29369902.349 119.0099912.249117.90629922.148117.65939925.448118.5027
9928.748120.06479938.648122.11759955.148121.71179965.048122.00969971.647121.1874
9974.947119.87199978.247117.23839981.547115.29519984.847114.18389991.447113.1062
9998.047112.902410007.98 113.73910027.84117.815910034.46118.640510044.38118.5957
10064.22120.253110093.98121.0639 10110.6126.524610127.24130.828810148.38139.0203
#Mann= 3 , 0 , 0
9808.203    0.12       09808.203    0.12       010148.38    0.12       0
#XS Ineff= 2 , 0
       09971.066        10021.51       0
Bank Sta=9808.203,10148.38
Exp/Cntr=0.3,0.1

Type RM Length L Ch R = 1 ,1897.655,92.683600,92.683600,92.683600
XS GIS Cut Line= 6
1291285.45841115627817.5394247981291264.26204883627727.584927434
1291238.18760967627593.3191302881291233.63335411627573.027944444
1291213.35916834627486.5007046951291200.25722089627440.110119623
#Sta/Elev= 30
9749.012138.36429769.155135.38519775.896132.81659786.008131.40029809.603124.5145
9816.344 122.7949826.456121.48579843.294118.25139860.004115.61199873.345112.7493
9903.452107.95729910.136107.22749920.163106.62849930.189105.48389943.557102.9801
9953.584102.12379960.268101.22879987.05999.7167610003.88 99.8533 10024.199.48321
10054.43101.426910061.17100.444210064.54100.488110071.28 101.09510078.37 102.975
10091.54107.316210094.94 108.13510101.76109.273310111.99 112.07710136.08120.1756
#Mann= 3 , 0 , 0
9749.012  0.0589       09749.012  0.0589       010136.08  0.0589       0
#XS Ineff= 2 , 0
       09967.289        10049.11       0
Bank Sta=9749.012,10136.08
Exp/Cntr=0.3,0.1

Type RM Length L Ch R = 1 ,1804.972,92.683600,92.683600,92.683600
XS GIS Cut Line= 6
1291381.89374554627797.8406603621291325.57623842627612.832128696
1291320.93891208627579.5160770081291325.04264098627539.358090656
1291321.25199034627514.852121854 1291269.8568389627411.787157201
#Sta/Elev= 30
9749.076117.37719762.775117.63899786.917116.28789804.162117.53099814.509117.1387
9821.407 115.1329828.305112.00899835.203109.8105 9845.55105.41979852.448103.0458
9855.897102.53419862.795101.96129883.353102.61239910.52998.807049937.70495.74561
9961.01294.921129970.94994.999129976.16294.484559987.40692.424899997.34692.07963
 10007.392.9677510020.5492.78172 10041.491.6184310058.1192.0462110075.8793.75536
10083.6894.9481410109.61101.027610118.24102.657110146.66110.774410156.65114.1123
#Mann= 3 , 0 , 0
9749.076  0.1012       09749.076  0.1012       010156.65  0.1012       0
#XS Ineff= 2 , 0
       09957.311        10078.45       0
Bank Sta=9749.076,10156.65
Exp/Cntr=0.3,0.1

Type RM Length L Ch R = 1 ,1712.288,92.683700,92.683700,92.683700
XS GIS Cut Line= 6
1291543.64935688627697.2796139011291492.61118636627604.600279229
1291452.77775964627551.4205842811291417.10642485627520.758884102
1291342.31082656627478.6616347661291287.31991299627402.085449374
#Sta/Elev= 30
9749.079107.75359763.327107.64749770.408106.83539772.479106.00189776.181103.4301
9783.58596.188719787.28794.25306 9790.9993.95616  9809.594.713139836.11795.03537
9839.93294.651749843.74892.916729847.563 91.88169863.15390.470539879.049 91.0758
9908.12289.590449917.87589.603869930.16187.959519941.23688.658539985.796 88.3981
9999.46786.98493 10006.687.6899510024.8488.1286910044.7989.5873810062.3592.49507
10075.59 95.727910088.6397.6833910112.23102.372610143.09 111.83110149.43113.2004
#Mann= 3 , 0 , 0
9749.079  0.1016       09749.079  0.1016       010149.43  0.1016       0
#XS Ineff= 2 , 0
       09936.993        10065.85       0
Bank Sta=9749.079,10149.43
Exp/Cntr=0.3,0.1

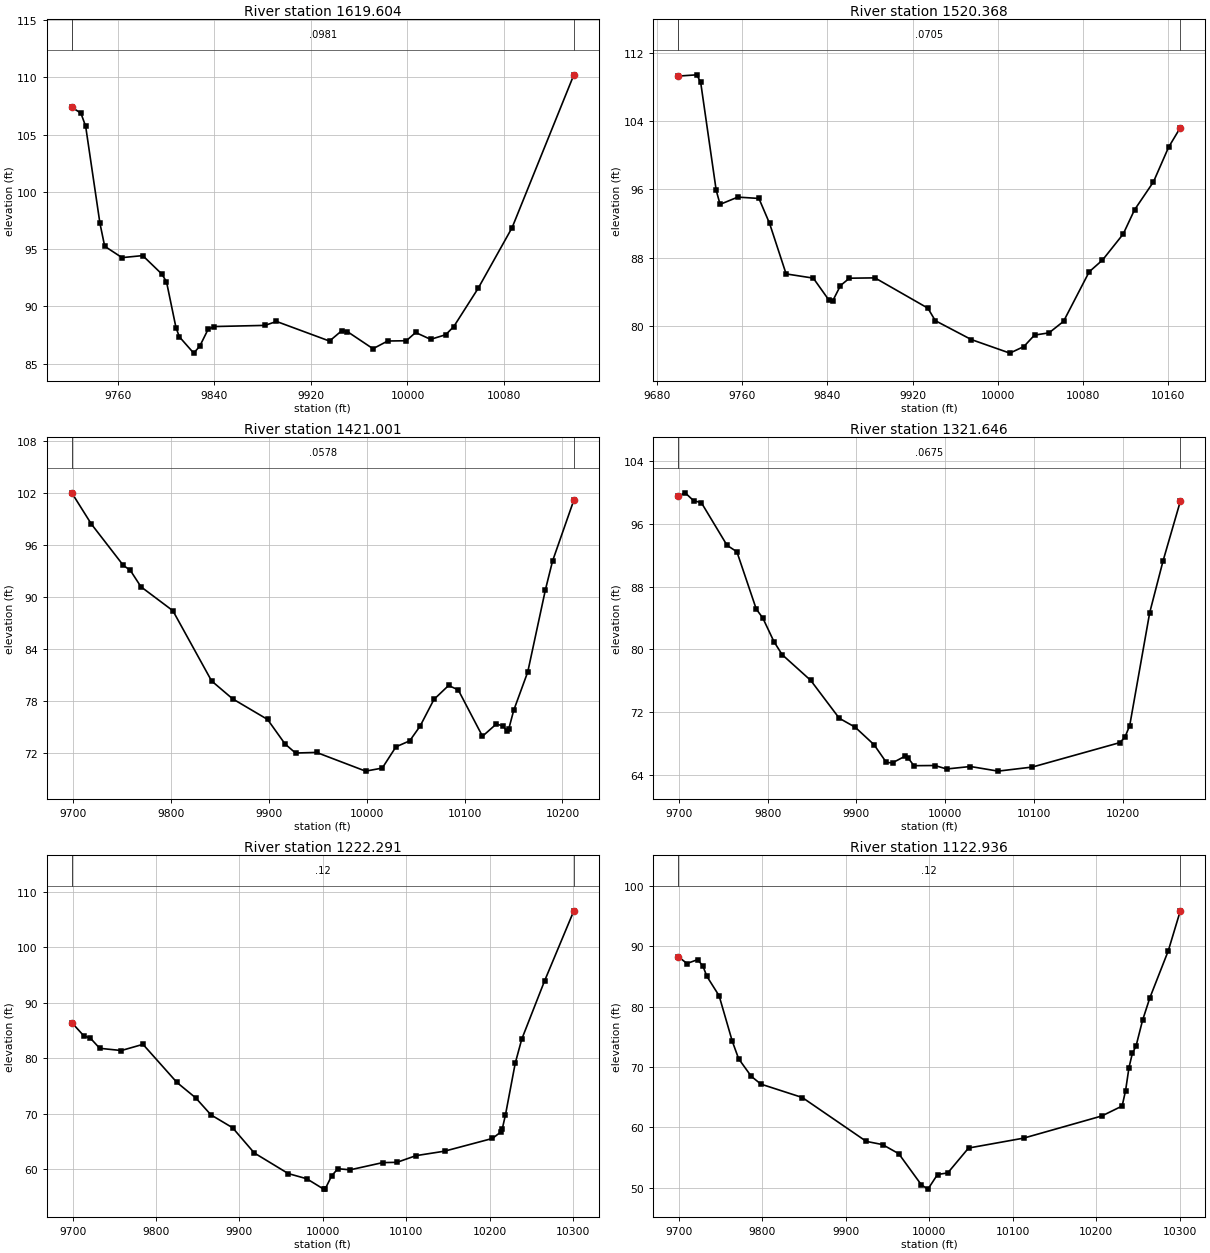
Type RM Length L Ch R = 1 ,1619.604,99.237000,99.237000,99.237000
XS GIS Cut Line= 6
1291609.28092545627669.7194740771291522.85760915627539.471900836
1291461.09207588627461.8382601141291439.27391836627426.444677979
1291396.17498049627365.7498142571291372.30902454627328.599251837
#Sta/Elev= 30
9722.033107.38239729.594106.87369733.532105.72289745.34497.263939749.28195.25122
9763.66894.258149780.78194.43584 9796.5392.832559800.468 92.15329808.34288.13677
9811.13987.342969823.00785.920649828.02986.530169834.87587.991519839.84288.24174
9882.04288.342339891.53988.686369935.44486.974579945.78187.893229950.22387.80075
9971.45386.305369983.62386.978559999.04787.0021110006.7487.7223610019.16 87.1233
10031.6287.5261510038.3588.2400210058.47 91.568110086.6496.8779610137.76110.2177
#Mann= 3 , 0 , 0
9722.033  0.0981       09722.033  0.0981       010137.76  0.0981       0
#XS Ineff= 2 , 0
       09961.099         10022.9       0
Bank Sta=9722.033,10137.76
Exp/Cntr=0.3,0.1

Type RM Length L Ch R = 1 ,1520.368,99.366200,99.366200,99.366200
XS GIS Cut Line= 6
1291646.94894846627675.805567187 1291554.5054982627482.136507728
1291538.49743254627432.858402292 1291531.0961444627367.425262127
1291517.75536766627320.8164759111291482.63492157627236.566776716
#Sta/Elev= 30
9699.725 109.3159717.163109.46329720.815108.58659735.42295.894349739.07494.24677
9755.73795.100619775.59294.94308 9785.6292.006479801.15586.079339826.718 85.5851
9841.32583.016519844.97782.907959852.28184.710999860.67585.574739884.68185.61444
9934.44982.056359941.42180.589439975.21178.3732410011.5476.7747610024.7477.54939
10034.7378.8950110048.38  79.15610062.0380.5073510086.1486.3260410098.6587.70667
10118.1290.7624910128.7893.6076710146.55 96.885210160.76100.947810171.82103.2592
#Mann= 3 , 0 , 0
9699.725  0.0705       09699.725  0.0705       010171.82  0.0705       0
#XS Ineff= 2 , 0
       09972.306        10038.93       0
Bank Sta=9699.725,10171.82
Exp/Cntr=0.3,0.1

Type RM Length L Ch R = 1 ,1421.001,99.355300,99.355300,99.355300
XS GIS Cut Line= 6
1291744.25850527627645.4726722311291692.25994496627533.655259492
1291630.01134085627388.6908533431291610.03159973627334.599881323
1291566.30760028627226.2829934211291542.23434734627174.559027692
#Sta/Elev= 30
9699.017102.01819719.02598.414229751.58993.655749758.82693.06818 9769.6891.17536
9802.24488.415119841.785 80.31319863.208 78.25289898.91375.872079916.76673.04291
9927.47771.997429948.90172.06817    999969.9095210016.0270.2604910029.9972.71212
10044.0473.4047610054.6675.1033610068.8178.1860310083.7479.7911710093.5879.28292
10118.3473.9327410132.4975.3461110139.5775.1022810143.11 74.530610145.0974.73834
10150.1976.9103710164.5681.3538110182.6590.8626510189.8994.1527410211.62101.1749
#Mann= 3 , 0 , 0
9699.017  0.0578       09699.017  0.0578       010211.62  0.0578       0
#XS Ineff= 2 , 0
       09949.103         10032.1       0
Bank Sta=9699.017,10211.62
Exp/Cntr=0.3,0.1

Type RM Length L Ch R = 1 ,1321.646,99.355200,99.355200,99.355200
XS GIS Cut Line= 6
1291829.97754221627621.2708247071291737.49079354627419.469112864
1291721.86419447627371.7352591331291709.33245935627306.474975391
1291688.46803011627251.6248091071291611.56552935627101.818115458
#Sta/Elev= 30
9699.06999.556589706.91299.964719716.32798.963839725.12498.708939754.09393.26522
 9765.1992.440469787.044 85.12189794.32984.002079806.96480.973839816.183 79.3141
9848.44776.023039880.57371.19543 9898.4270.061429919.83767.813399933.68865.55163
9940.59265.507589954.40166.333779957.853 66.17139964.75765.140589988.32265.16387
10001.64 64.721510028.3865.0364910059.6164.4472410098.2864.96885 10196.768.08216
10202.48 68.754410207.9770.2654310230.5284.6858410245.55 91.2769   1026598.87893
#Mann= 3 , 0 , 0
9699.069  0.0675       09699.069  0.0675       0   10265  0.0675       0
#XS Ineff= 2 , 0
       09957.432        10048.01       0
Bank Sta=9699.069,10265
Exp/Cntr=0.3,0.1

Type RM Length L Ch R = 1 ,1222.291,99.355300,99.355300,99.355300
XS GIS Cut Line= 6
1291940.71219666627561.8533332991291801.30967128 627296.22588476
1291800.30623505 627294.495822411291762.82946186627224.984945396
1291708.69298383627132.4156519431291647.15769688627036.721387932
#Sta/Elev= 30
9699.01586.456379713.39684.066649721.40483.63766 9732.5281.818139758.45681.41767
9784.39282.533059825.14975.660279847.53872.898929865.90669.827559891.843 67.5073
9917.77962.972169958.53659.255239980.76758.31878   10001 56.451510003.0656.54491
10010.5158.8165310017.9760.1261210032.8859.93134 10071.861.2272210088.9661.28053
10111.7662.4833710145.9763.2886410203.3965.58121 10213.466.74608 10215.167.25734
   1021969.82965 10230.779.12622 10238.5 83.4564 10265.893.9274810300.98106.5833
#Mann= 3 , 0 , 0
9699.015    0.12       09699.015    0.12       010300.98    0.12       0
#XS Ineff= 2 , 0
       09955.161        10048.24       0
Bank Sta=9699.015,10300.98
Exp/Cntr=0.3,0.1

Type RM Length L Ch R = 1 ,1122.936,99.355200,99.355200,99.355200
XS GIS Cut Line= 6
1292044.36121845627509.1298688361291939.96518776627333.361537813
 1291888.5880779627252.8086217151291882.09405369627241.934923864
1291830.11776331627174.8413858591291708.96381925627010.180044264
#Sta/Elev= 30
9699.02488.302539709.49187.15665 9722.34 87.80479728.76586.694639733.26285.05338
9748.03981.807759763.78974.296529771.42171.384389786.58768.473069798.13267.18164
9847.73864.965129924.46457.69758 9943.92 57.16849963.37755.661489990.61650.48303
9998.39949.7898610009.8752.2095410022.1752.4780510047.0756.5936310113.1658.23592
10206.8561.9051510231.2263.5528310235.3666.1194510239.4369.91483 10243.572.30112
10247.8273.4533210255.7277.7573810264.4381.4668810286.5789.2766410300.9795.88207
#Mann= 3 , 0 , 0
9699.024    0.12       09699.024    0.12       010300.97    0.12       0
#XS Ineff= 2 , 0
       09939.671        10057.56       0
Bank Sta=9699.024,10300.97
Exp/Cntr=0.3,0.1

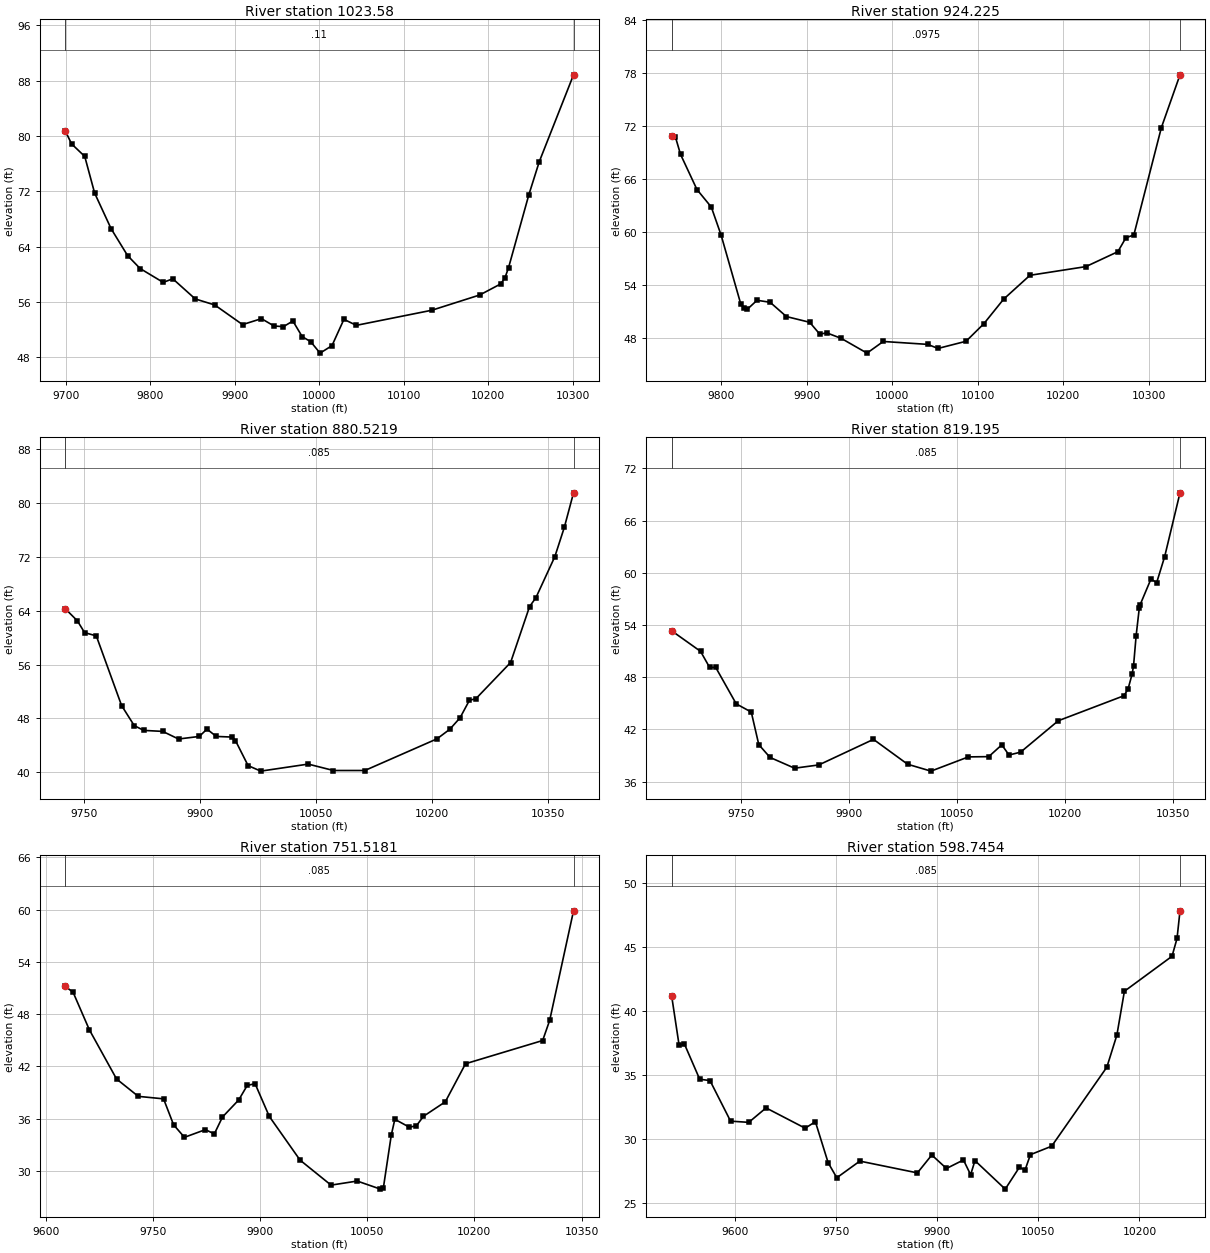
Type RM Length L Ch R = 1 , 1023.58,99.355300,99.355300,99.355300
XS GIS Cut Line= 6
1292101.48256177627446.6525055861292015.95624118627307.557135614
1291962.13244668627207.3159419171291914.98946346627107.140503609
1291866.05028057627041.7400534151291775.91911769626945.220675731
#Sta/Elev= 30
9699.04880.749129706.57678.852279722.18577.037259733.89271.739849753.40366.59269
9772.91462.707949787.70860.842929815.06558.836969826.44959.354389853.01456.44516
9876.04855.576759909.04752.73649 9931.3953.595159946.28552.537399957.45752.44035
9968.62953.256579979.62351.002379989.75750.2629510000.8248.6140110014.9349.69705
10029.0553.4984510043.7452.6289310133.1454.8120110189.89 57.017510214.4958.60287
10219.5359.4400410223.9360.9384610247.9871.4881910260.3576.2786810300.9288.82998
#Mann= 3 , 0 , 0
9699.048    0.11       09699.048    0.11       010300.92    0.11       0
#XS Ineff= 2 , 0
       09919.198        10038.01       0
Bank Sta=9699.048,10300.92
Exp/Cntr=0.3,0.1

Type RM Length L Ch R = 1 , 924.225,43.703100,43.703100,43.703100
XS GIS Cut Line= 6
1292185.37132496627401.3934544621292110.00387341627274.729043782
1292067.29106063627211.0068569481292052.96477291627186.620442301
 1291998.5304991 627122.79127261 1291817.3972449626939.250724077
#Sta/Elev= 30
9742.334 70.83249746.66570.752239752.65968.775079771.90764.786419788.65962.80538
9800.11259.631489823.01951.859079826.83651.344949830.65451.227989842.107 52.2535
9857.37852.029019876.46650.410689903.65649.762639915.50548.412059923.40448.57275
9940.61947.938019970.63846.272629989.64147.59205 10041.547.2629810053.6746.80316
10086.3747.6143110107.27 49.605710130.3152.37877 10161.155.0813410226.4956.06485
10263.8557.7534710273.1959.3234810282.5459.6507110314.6971.7945510336.4877.77259
#Mann= 3 , 0 , 0
9742.334  0.0975       09742.334  0.0975       010336.48  0.0975       0
#XS Ineff= 2 , 0
       0  9971.8        10062.52       0
Bank Sta=9742.334,10336.48
Exp/Cntr=0.3,0.1

Type RM Length L Ch R = 1 ,880.5219,61.326900,61.326900,61.326900
XS GIS Cut Line= 2
1292247.58954695627380.7172331361291854.79440805626853.373483136
#Sta/Elev= 30
 9725.6564.312099741.32762.515899750.76860.749019765.87360.269099798.60149.89953
9814.96446.920389827.23746.208939851.78346.060959872.23744.927349899.05945.30969
9909.056 46.40179921.02845.311479941.78345.216119945.87444.696729962.23840.97049
9978.60240.1507410039.9741.1961610072.6940.2432810113.2640.2439110206.6244.95443
 10223.146.3735710236.3348.06623 10248.650.7001710256.7950.9084210301.79  56.304
10326.3364.6260710334.5165.9384310359.0672.0637810371.3376.4227410383.2181.54631
#Mann= 3 , 0 , 0
 9725.65   0.085       0 9725.65   0.085       010383.21   0.085       0
#XS Ineff= 2 , 0
       09972.563        10056.34       0
Bank Sta=9725.65,10383.21
Exp/Cntr=0.3,0.1

Type RM Length L Ch R = 1 , 819.195,67.676900,67.676900,67.676900
XS GIS Cut Line= 4
1292344.78343698627366.5669216071292165.96399257 627145.21275495
1292062.66538143627069.6919216071291892.12079698626829.935983136
#Sta/Elev= 30
9653.52853.323429693.67750.96319 9706.3349.110229714.76549.116599743.31744.92503
  9764.243.986479774.64240.242659790.30538.771249824.423 37.53459858.16537.91093
9934.08240.848619981.54937.9902110014.06 37.197610066.0538.8338610094.3638.86319
10112.51 40.219110122.5439.0486110138.6539.3795610190.9942.9862510282.3145.86184
10287.9746.6131710293.6348.3320310295.6749.2901910299.2952.7756210303.7255.97373
10304.9556.3438910319.8359.2646310327.88 58.875310338.9161.8400810360.2769.18361
#Mann= 3 , 0 , 0
9653.528   0.085       09653.528   0.085       010360.27   0.085       0
#XS Ineff= 2 , 0
       09948.411        10046.35       0
Bank Sta=9653.528,10360.27
Exp/Cntr=0.3,0.1

Type RM Length L Ch R = 1 ,751.5181,152.772700,152.772700,152.772700
XS GIS Cut Line= 4
1292357.80427036627344.8655327261292213.70704812 627098.33775495
1292073.95010367626995.9071993681291905.14163035626808.234594256
#Sta/Elev= 30
9627.48851.186249638.52650.505989661.327 46.18849699.32940.54475 9729.7338.54781
9765.10438.262159779.13235.280869794.33333.841829823.61834.724469836.135 34.2338
9847.53636.172989870.33738.143499882.13139.796869893.13840.00896 9913.04 36.2458
9956.12331.220759999.46128.3500410036.0728.8183810068.6127.8899910072.6828.04507
10083.7734.1198810088.7135.9130610109.1235.0016310118.9335.1743710128.7436.25425
10159.3137.9205210187.6142.2959110295.5444.9638910305.3547.2734410338.7459.86216
#Mann= 3 , 0 , 0
9627.488   0.085       09627.488   0.085       010338.74   0.085       0
#XS Ineff= 2 , 0
       09927.791        10067.24       0
Bank Sta=9627.488,10338.74
Exp/Cntr=0.3,0.1

Type RM Length L Ch R = 1 ,598.7454,92.994200,92.994200,92.994200
XS GIS Cut Line= 6
1292442.05002266627302.1847518681292340.48752269627131.611835197
1292164.94878799626921.2111804191292123.55152541626888.104436308
1292089.80255625626865.6803674551291923.59255069626776.761116594
#Sta/Elev= 30
9505.67841.201129516.73337.34781 9524.3737.48055 9547.28 34.70059562.55434.59732
9593.10131.426879620.11631.331579645.76732.461619703.83330.876279718.99131.38148
9737.97228.17528 9750.7927.003919784.97228.304389870.42727.38446 9891.7928.78097
  9913.627.72868 9938.79 28.39389949.44927.240229955.88128.3416810000.8126.11531
10021.8327.8219410030.2327.6076910038.1728.8067610069.6929.4684110151.6635.64369
10166.5438.14953 10177.741.57421 10248.444.3083810255.8445.6997710260.2447.85821
#Mann= 3 , 0 , 0
9505.678   0.085       09505.678   0.085       010260.24   0.085       0
#XS Ineff= 2 , 0
       09895.203        10042.69       0
Bank Sta=9505.678,10260.24
Exp/Cntr=0.3,0.1

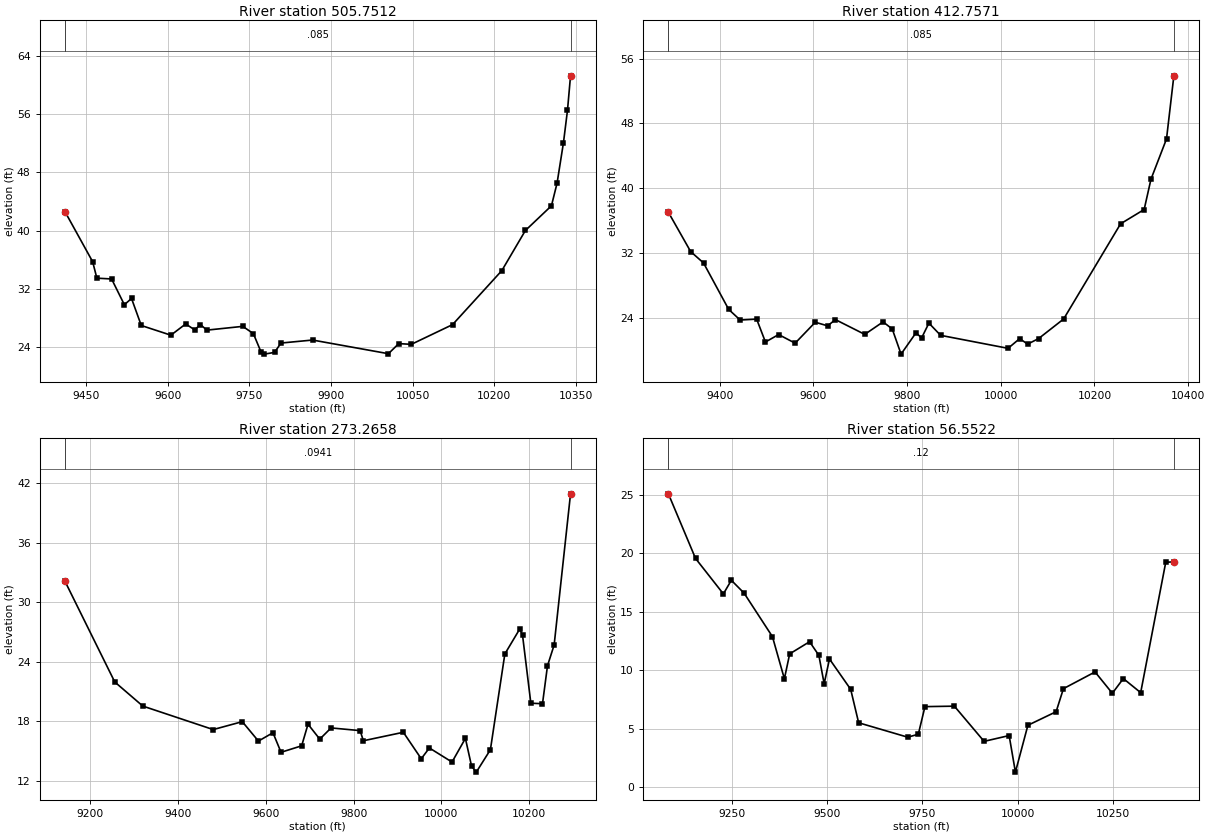
Type RM Length L Ch R = 1 ,505.7512,92.994100,92.994100,92.994100
XS GIS Cut Line= 6
1292541.00835603627325.6222518681292255.85210603626877.705585182
1292223.38653532626847.5502125021292128.77475375626790.965798602
1291980.48929298626720.8228014111291909.36928731626684.264394045
#Sta/Elev= 30
9410.95342.582559461.66635.723389469.44433.455259496.52733.348299520.00529.80616
9533.18230.665299551.11926.949829605.56925.617649632.79427.163169649.25726.35373
9660.01927.073679671.68626.312469737.80426.82995 9757.2525.83386 9771.4423.29386
9777.54923.012569796.14323.252649808.09524.53649 9866.1524.9494810005.6123.07052
10024.5924.4570110047.7424.3592510123.5927.07009 10214.2 34.496110257.5640.01404
10305.4543.4090410315.82 46.530910327.5852.1001410334.9656.5449610340.56 61.2786
#Mann= 3 , 0 , 0
9410.953   0.085       09410.953   0.085       010340.56   0.085       0
#XS Ineff= 2 , 0
       09956.559        10033.97       0
Bank Sta=9410.953,10340.56
Exp/Cntr=0.3,0.1

Type RM Length L Ch R = 1 ,412.7571,139.491300,139.491300,139.491300
XS GIS Cut Line= 6
1292650.38335603627355.5701685251292260.29630628626762.515542045
1292241.96985367626749.0670394451292104.06812307626717.683352292
1292028.61715269626690.5419723691291916.78086674626637.481594414
#Sta/Elev= 30
9290.757 37.05359338.33632.204159365.70830.81247 9419.4625.081239443.91623.77517
9479.10923.887829497.84521.066159526.03321.984599561.22720.921869604.24123.50365
9630.49723.058119647.255 23.82479709.82122.006029748.92523.546439768.47622.66836
9787.26719.572999819.31122.213979831.04221.555469846.68423.394929871.68221.88801
10015.5920.2869410040.4821.4871910057.2820.8045310080.6321.4832110134.25 23.9039
10255.7635.6338110306.0337.3935210320.5941.1306510353.7546.0929710369.4353.86812
#Mann= 3 , 0 , 0
9290.757   0.085       09290.757   0.085       010369.43   0.085       0
#XS Ineff= 2 , 0
       09958.429        10062.14       0
Bank Sta=9290.757,10369.43
Exp/Cntr=0.3,0.1

Type RM Length L Ch R = 1 ,273.2658,216.713600,216.713600,216.713600
XS GIS Cut Line= 6
1292680.33127266627347.7576685251292351.68543938626700.969474077
1292255.42357954626650.0338647221292142.01003447626614.234533668
1292063.60018572626575.5229923871291967.33535558626519.630491376
#Sta/Elev= 30
9142.12132.086439255.41621.970979319.36919.54431  9479.9 17.18089546.14217.97723
9582.94216.022879616.06316.862039634.46314.894459681.49615.545919695.98117.72164
9722.785 16.21789748.54617.346259814.78717.075359822.14716.055379913.27816.90768
9954.10814.245069972.66715.3297610024.2813.9119610054.7916.2928410068.8913.49306
10079.6112.8982910111.77 15.1536 10144.724.7871310178.7627.3096810185.0226.68043
10203.9819.8335310230.5419.7821910241.9223.59651 10257.125.6971310294.4640.90329
#Mann= 3 , 0 , 0
9142.121  0.0941       09142.121  0.0941       010294.46  0.0941       0
#XS Ineff= 2 , 0
       0  9918.1        10038.33       0
Bank Sta=9142.121,10294.46
Exp/Cntr=0.3,0.1

Type RM Length L Ch R = 1 , 56.5522,0.000000,0.000000,0.000000
XS GIS Cut Line= 6
1292681.63335603627313.9035018531292456.72016159626667.549335182
1292371.36621121626505.6733926831292323.72958374626442.235780299
1292215.66611838626325.342041224  1292041.789606626193.591001853
#Sta/Elev= 30
9084.36425.090089155.463 19.56769228.41316.535029249.25617.700059282.72716.59807
9356.943 12.87869388.2079.2752999402.10211.408389454.20912.445949478.52611.28238
9492.4218.8509299506.31610.970069561.8978.3752559582.7395.517058 9711.274.285243
 9739.064.5361729756.4296.8972889833.4846.9377869911.3733.9281059977.0064.424344
 9993.411.29796210026.095.30364610100.076.46227510119.17 8.4331910202.039.863211
10247.318.03930410276.139.29518510321.548.09422310387.2719.2466810408.4819.26735
#Mann= 3 , 0 , 0
9084.364    0.12       09084.364    0.12       010408.48    0.12       0
#XS Ineff= 2 , 0
       09973.897        10035.66       0
Bank Sta=9084.364,10408.48
Exp/Cntr=0.3,0.1